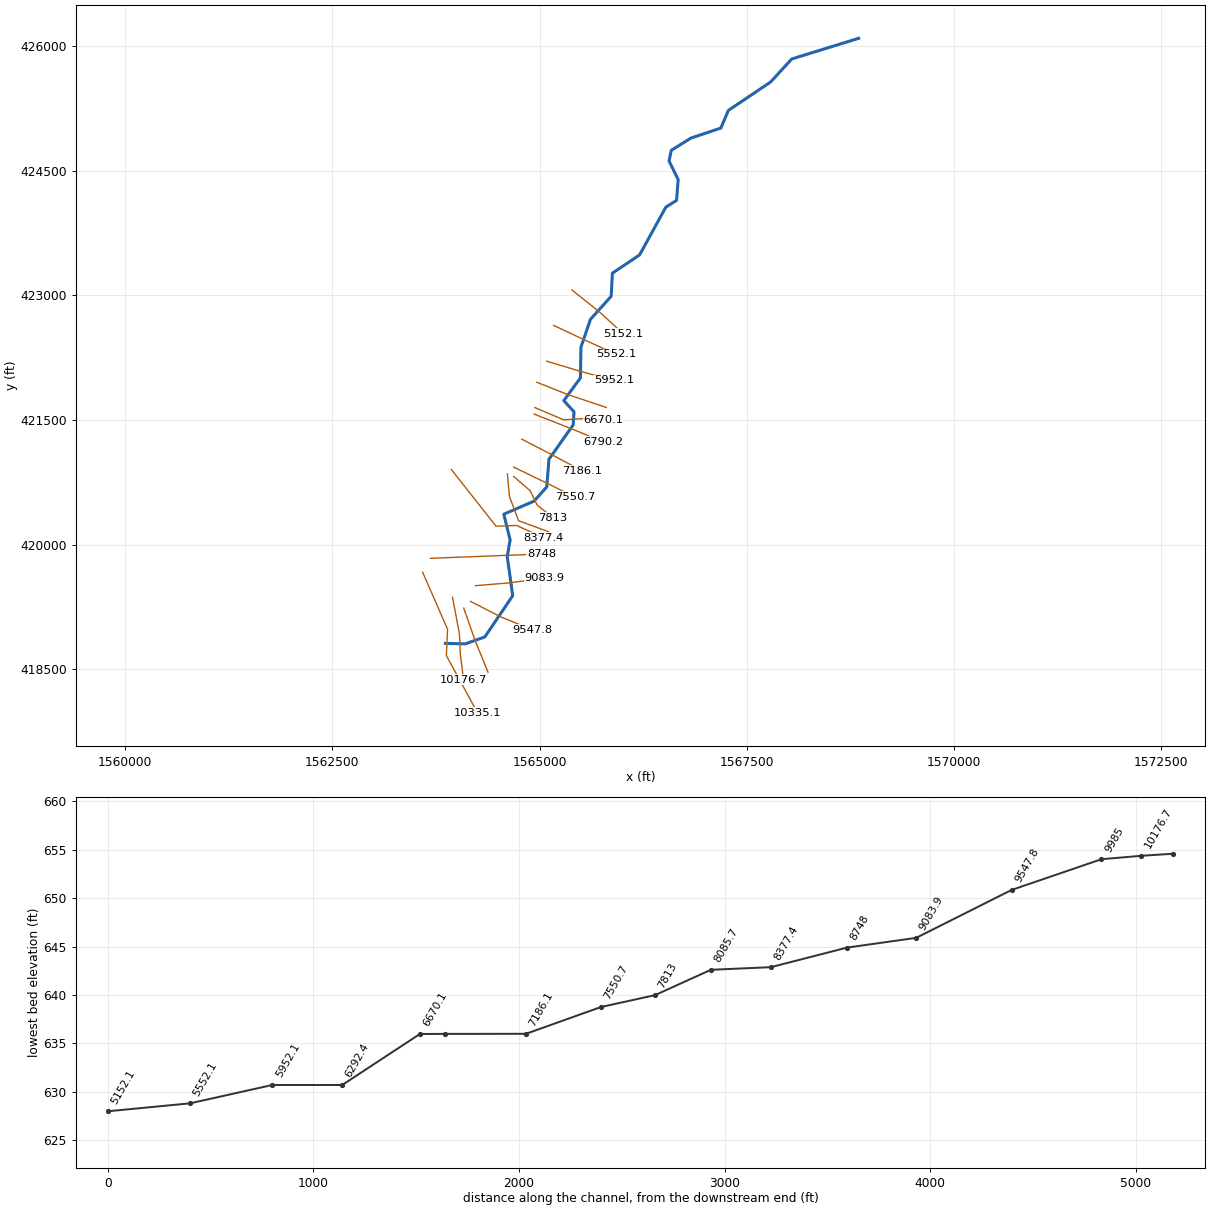
--- CENLYNNCR.prj (project) ---

Proj Title=CENLYNNCR
Current Plan=p01
Default Exp/Contr=0,0
English Units
Geom File=g01
Flow File=f01
Plan File=p01
BEGIN DESCRIPTION:
END DESCRIPTION:
DSS Export Rating Curves= 0
DSS Export Rating Curve Sorted= 0
DSS Export Volume Flow Curves= 0
DXF OffsetX= 0
DXF OffsetY= 0
DXF ScaleX= 0
DXF ScaleY= 0

--- CENLYNNCR.p01 (plan) ---

Plan Title=Floodplain
Program Version=4.00
Geom File=g01
Flow File=f01
K Sum by GR=0
Std Step Tol=0.01
Critical Tol=0.01
Num of Std Step Trials=20
Max Error Tol=0.3
Flow Tol Ratio=0.001
Split Flow NTrial=30
Split Flow Tol=0.02
Split Flow Ratio=0.02
Log Output Level=0
Friction Slope Method=1
Unsteady Friction Slope Method=2
Unsteady Bridges Friction Slope Method=1
Global Log Level=0
CheckData=False
Run HTab=0
Run UNet=0
Run PostProcess=0
UNET Theta=0
UNET Theta Warmup=0
UNET ZTol=0
UNET ZSATol=0
UNET MxIter=0
UNET MaxInSteps=0
UNET DtIC=0
UNET DtMin=0
UNET MaxCRTS=0
UNET WFStab=0
UNET SFStab=0
UNET WFX=0
UNET SFX=0
UNET DSS MLevel=0
UNET DZMax Abort=0
UNET Convert EG Bridges=0
UNET Use Existing IB Tables=0
UNET Froude Limit=0
UNET Froude Power=0
Write IC File=0
Echo Input=False
Echo Output=False
Write Detailed=0

--- CENLYNNCR.f01 (steady flow) ---

Flow Title=NFF Regression Equation
Program Version=4.00
Number of Profiles= 1
Profile Names=P100yr
River Rch & RM=CENLYNNCR,Main            ,10335.1
     536
River Rch & RM=CENLYNNCR,Main            ,10176.7
     834
River Rch & RM=CENLYNNCR,Main            ,8377.4
     858
River Rch & RM=CENLYNNCR,Main            ,8085.7
     960
River Rch & RM=CENLYNNCR,Main            ,7186.1
     994
Boundary for River Rch & Prof#=CENLYNNCR,Main            , 1
Up Type= 0
Dn Type= 3
Dn Slope=0.002258
DSS Import GetInterval= 0
DSS Import GetPeak= 0
DSS Import FillOption= 0

--- CENLYNNCR.g01 (geometry) ---

Geom Title=USGS 10m DEM
Program Version=4.00

River Reach=CENLYNNCR       ,Main
Reach XY= 30
     1563864.431      418812.882     1564103.089      418806.616
     1564339.847      418890.002      1564676.37      419385.852
     1564610.852      419856.388       1564645.1      420057.409
     1564569.159      420367.129     1564933.974      420523.478
     1565087.345      420694.718     1565114.147      421028.263
     1565405.999      421440.727     1565416.422      421598.565
     1565292.832      421732.579     1565493.853      422006.562
     1565499.809      422374.355     1565614.465      422710.878
     1565864.623      422987.839     1565879.514       423266.29
     1566207.103      423485.179     1566524.268      424059.948
     1566653.814      424141.845     1566673.172      424392.004
     1566562.983       424615.36     1566589.786      424743.417
     1566826.543      424890.832      1567188.38      425011.444
     1567279.211      425224.377     1567788.463      425565.367
     1568043.088      425842.328     1568850.933      426091.373

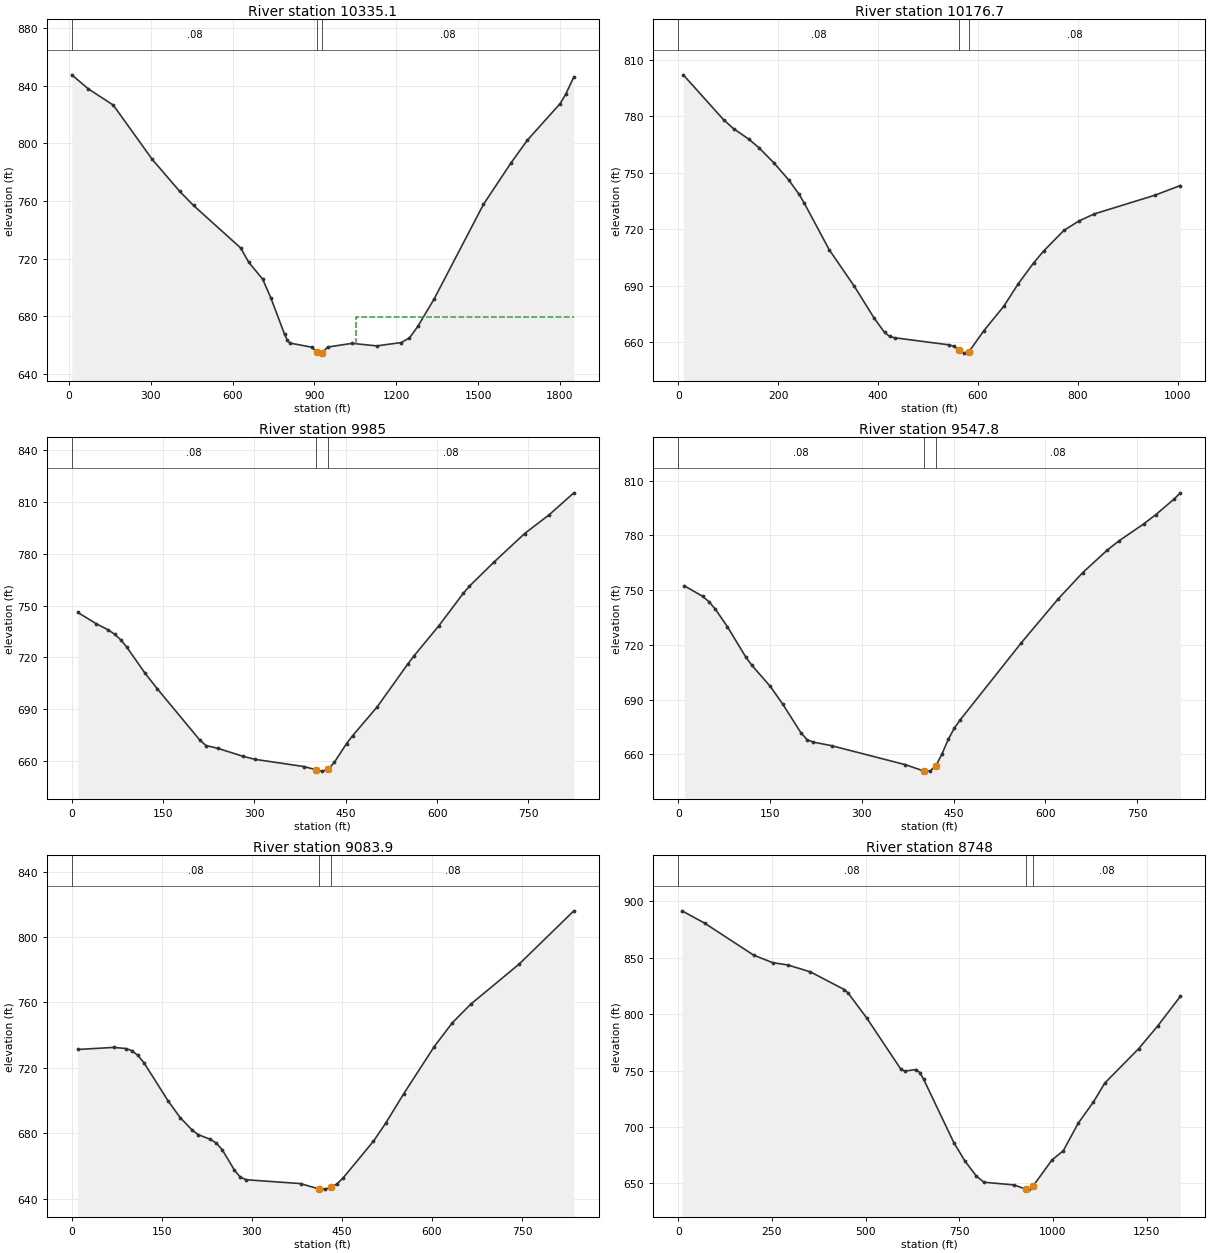
Type RM Length L Ch R = 1 ,10335.1 ,156.1,158.4,160.7
XS GIS Cut Line= 4
      1563588.74      419670.045     1563890.475      418982.484
     1563875.635      418665.909     1564251.568      417978.349
#Sta/Elev= 30
    10.1  847.57      71  837.82   162.3  826.59   304.4  789.15   405.9  766.76
   456.6  756.97   629.1  727.56   659.5  717.47   710.3  705.88   740.7  692.63
   790.5  667.63   800.4   663.6   810.3  661.55   889.5  658.69   909.2  655.58
   919.2  654.57   929.2     655   948.9  658.79  1038.1  661.35  1128.1  659.59
  1218.5   661.9  1248.6  665.13  1278.8  673.04    1339  692.14  1519.9  757.71
  1620.3  786.32  1680.6   802.2  1801.2  827.63  1821.3  834.04  1851.4  846.12
#Mann= 3 , 0 , 0
    10.1     .08       0   909.2    .045       0   929.2     .08       0
#XS Ineff= 2 , 0
                         1051.45          679.36
Permanent Ineff=
       F       F
Bank Sta=909.2,929.2
XS Rating Curve= 0 ,0
Exp/Cntr=0.3,0.1

Type RM Length L Ch R = 1 ,10176.7 ,184.1,191.7,200.3
XS GIS Cut Line= 4
     1563949.833       419368.31     1564033.923      418923.126
     1564043.816      418685.695     1564083.388      418374.067
#Sta/Elev= 30
    10.1  801.96    90.6  778.18   110.7  773.41     141   767.9   161.1  763.39
   191.3  755.31   221.5  746.09   241.6  738.67   251.7  734.18     302  709.25
   352.4  689.81   392.6  672.72   412.8  665.35   422.9  663.26   432.9   662.5
   542.2  658.73   552.1   657.9   561.9  656.03   571.9  654.35   581.9  655.12
   611.5  666.22   651.1  679.09   680.8  691.26     711  702.13   731.2  708.48
   771.8  719.45   802.2  724.48   832.6  728.18   954.2  738.13  1004.8  743.24
#Mann= 3 , 0 , 0
       0     .08       0   561.9    .045       0   581.9     .08       0
Bank Sta=561.9,581.9
XS Rating Curve= 0 ,0
Exp/Cntr=0.3,0.1

Type RM Length L Ch R = 1 ,9985    ,418.2,437.2,456.7
XS GIS Cut Line= 3
      1564086.01      419236.721     1564221.889      418848.929
     1564378.391      418466.024
#Sta/Elev= 30
      10  745.99    40.1  739.49    60.1  735.85    70.2  733.42    80.2  730.23
    90.2  725.96   120.3  710.82   140.3  701.83   210.5  671.91   220.5  668.84
   240.5  667.18   280.6  662.64   300.7  660.85   380.8  656.67   400.9  654.84
   410.9     654   420.9  654.97   431.1  659.05   451.3  669.96   461.4   674.6
   501.7   691.3   552.2  716.28   562.2  720.89   602.6  738.15     643  757.09
     653   761.2   693.4  775.19   743.8  791.77   784.2  802.66   824.6  815.36
#Mann= 3 , 0 , 0
       0     .08       0   400.9    .045       0   420.9     .08       0
Bank Sta=400.9,420.9
XS Rating Curve= 0 ,0
Exp/Cntr=0.3,0.1

Type RM Length L Ch R = 1 ,9547.8  ,448.3,464,477.9
XS GIS Cut Line= 3
     1564167.775      419317.504     1564534.189      419131.021
     1564912.717      418975.554
#Sta/Elev= 30
      10  752.37    40.1   746.6    50.1  743.69    60.2  739.79    80.2  730.06
   110.3  713.39   120.3  708.82   150.4  697.28   170.5  687.68   200.6  671.79
   210.6  668.04   220.6  666.75   250.7  664.76     371  654.37   401.1  650.91
   411.1  650.83   421.1  653.82   431.1  660.36   441.1  668.21   451.1  674.39
     461  679.06   560.8  721.28   620.7  745.19   660.7  759.57   700.6  771.86
   720.5  777.13   760.5   786.3   780.4  791.45   810.4  799.99   820.3  803.35
#Mann= 3 , 0 , 0
       0     .08       0   401.1    .045       0   421.1     .08       0
Bank Sta=401.1,421.1
XS Rating Curve= 0 ,0
Exp/Cntr=0.3,0.1

Type RM Length L Ch R = 1 ,9083.9  ,338,335.8,333.5
XS GIS Cut Line= 3
     1564225.352      419506.514     1564605.241      419538.172
     1565056.938      419594.754
#Sta/Elev= 30
      10  731.25    70.2  732.52    90.3  731.82   100.3  730.49   110.3  727.58
   120.4  723.07   160.5  699.82   180.6   689.6   200.6  681.98   210.7   679.2
   230.7  676.33   240.8  674.08   250.8  669.88   270.9  657.54   280.9  653.13
   290.9  651.62   381.2  649.27   411.7     646   421.7  645.89   431.7  646.91
   441.9  649.11     452  652.71   502.6   675.2   522.8  686.11   553.2  704.31
   603.8  732.99   634.1  747.62   664.5  758.88   745.4  783.48   836.4  815.99
#Mann= 3 , 0 , 0
       0     .08       0   411.7    .045       0   431.7     .08       0
Bank Sta=411.7,431.7
XS Rating Curve= 0 ,0
Exp/Cntr=0.3,0.1

Type RM Length L Ch R = 1 ,8748    ,370.9,370.6,370.4
XS GIS Cut Line= 3
     1563684.009      419835.752     1564610.166      419872.158
      1565023.12      419886.404
#Sta/Elev= 30
    10.1   891.6    70.5  880.65   201.5  852.28   251.9  845.68   292.2  843.63
   352.6  837.51   443.3  821.77   453.4  818.79   503.7  796.31   594.4  751.11
   604.5  749.51   634.7   750.9   644.8  748.22   654.9  742.37   735.5   686.2
   765.7  669.53   795.9  656.43   816.1  651.01   896.6   648.6     927  644.92
     937  644.89     947  647.55   997.4   670.7  1027.7  678.87    1068  703.56
  1108.3  722.18  1138.5  738.88  1229.2   769.5  1279.6  789.47  1340.1  815.71
#Mann= 3 , 0 , 0
       0     .08       0     927    .045       0     947     .08       0
Bank Sta=927,947
XS Rating Curve= 0 ,0
Exp/Cntr=0.3,0.1

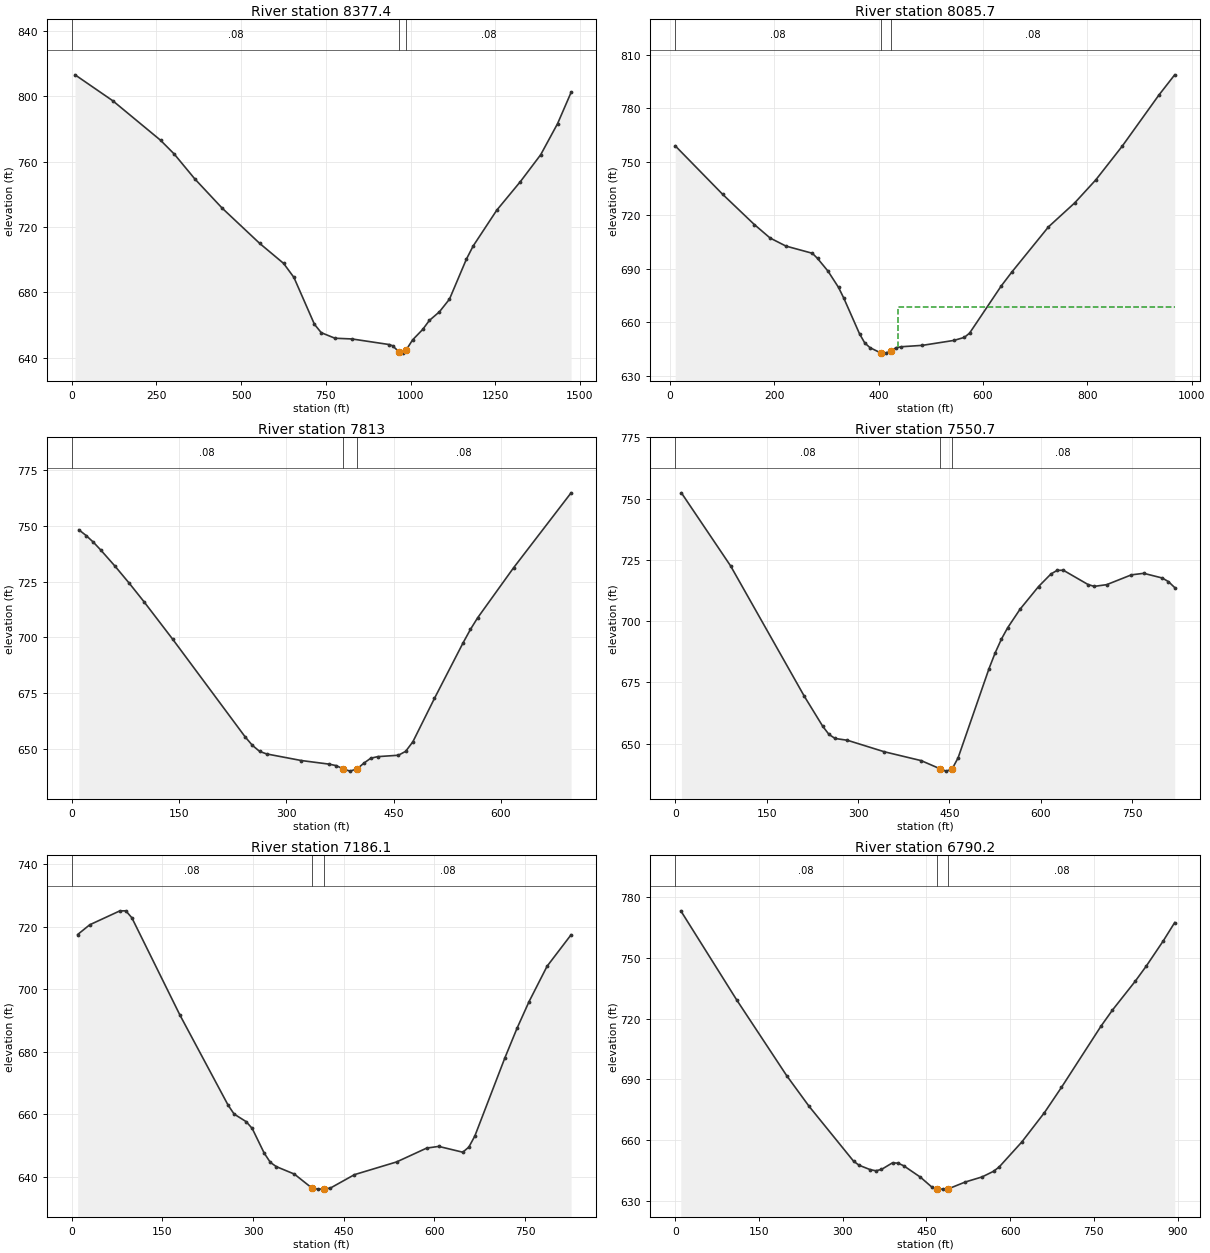
Type RM Length L Ch R = 1 ,8377.4  ,323.3,291.7,260.1
XS GIS Cut Line= 4
     1563937.269      420902.609     1564475.446      420221.973
     1564722.374      420231.471     1565049.012      420082.772
#Sta/Elev= 30
    10.1  812.99   121.1  797.18   262.3     773   302.7  764.57   363.2  749.42
   443.9  731.55   554.9  709.94   625.5   697.7   655.8  689.17   716.4   660.5
   736.5  655.37   776.9  651.98   827.3  651.53   936.9  648.12   946.8  647.39
   966.4  643.58   976.4  642.87   986.4   644.6  1006.1  650.98  1035.7  657.32
  1055.5  662.85  1085.2  668.13  1114.8  675.86  1164.7  700.28  1184.6  708.31
  1254.4  730.26  1324.2  747.75    1384  764.16  1433.8  783.16  1473.7  802.26
#Mann= 3 , 0 , 0
       0     .08       0   966.4    .045       0   986.4     .08       0
Bank Sta=966.4,986.4
XS Rating Curve= 0 ,0
Exp/Cntr=0.3,0.1

Type RM Length L Ch R = 1 ,8085.7  ,270.4,272.8,275.2
XS GIS Cut Line= 4
     1564612.367      420851.481     1564636.899      420579.703
       1564747.7      420288.454     1565107.058      420156.072
#Sta/Elev= 30
    10.1  758.98   101.1  731.73   161.7   714.8     192  707.22   222.3   702.7
   272.9  698.66   282.9  695.76     303  688.61   323.1  679.51   333.2  673.48
   363.4  653.44   373.4  648.31   383.5  645.66   403.6  642.78   413.6   642.6
   423.6     644   433.7  645.65   443.8  646.19     484  646.97   544.3  649.74
   564.4  651.45   574.4  653.86   634.9  680.26     655     688   725.6  713.49
     776  726.99   816.3  739.88   866.7   758.7   937.2  787.48   967.5  798.84
#Mann= 3 , 0 , 0
    10.1     .08       0   403.6    .045       0   423.6     .08       0
#XS Ineff= 2 , 0
                          437.57           668.7
Permanent Ineff=
       F       F
Bank Sta=403.6,423.6
XS Rating Curve= 0 ,0
Exp/Cntr=0.3,0.1

Type RM Length L Ch R = 1 ,7813    ,245.7,262.2,278.6
XS GIS Cut Line= 4
     1564687.551        420820.3     1564886.993      420649.349
     1564972.468      420475.233     1565162.413      420326.443
#Sta/Elev= 30
    10.1  748.27    20.2  745.71    30.3  742.73    40.4   739.3    60.6  731.96
    80.8  724.18     101  716.04   141.4  699.09   242.5  655.33   252.6  651.54
   262.7  648.83   272.4   647.7   320.9  644.74   359.7  643.12   369.4  642.47
   378.8  641.11   388.8  639.98   398.8  640.95   408.2  643.53   417.9  645.76
   427.6  646.48   456.6  647.11   466.7  648.85   476.8  653.15   506.9  672.58
   547.1  697.63   557.2  703.55   567.2  708.73   617.5  731.22   697.9  764.86
#Mann= 3 , 0 , 0
       0     .08       0   378.8    .045       0   398.8     .08       0
Bank Sta=378.8,398.8
XS Rating Curve= 0 ,0
Exp/Cntr=0.3,0.1

Type RM Length L Ch R = 1 ,7550.7  ,365.2,364.6,364
XS GIS Cut Line= 3
     1564688.428      420932.851     1565097.624      420735.836
      1565425.17      420573.371
#Sta/Elev= 30
    10.1  752.38    90.8  722.58   211.9  669.32   242.2  657.04   252.3  653.76
   262.4  652.09   282.6  651.36   343.1  646.67   403.7  643.05   434.1  639.78
   444.1  638.76   454.1  639.48   464.3  644.19   515.1  680.65   525.2  687.08
   535.4  692.66   545.6  697.28   565.9  704.84   596.3  714.11   616.7  719.25
   626.8  720.72     637  720.78   677.6  714.94   687.7  714.19   708.1  714.88
   748.7  718.89     769  719.52   799.5   717.6   809.6  716.12   819.8  713.71
#Mann= 3 , 0 , 0
       0     .08       0   434.1    .045       0   454.1     .08       0
Bank Sta=434.1,454.1
XS Rating Curve= 0 ,0
Exp/Cntr=0.3,0.1

Type RM Length L Ch R = 1 ,7186.1  ,393.4,395.9,398.5
XS GIS Cut Line= 3
     1564785.676      421269.248     1565148.783       421082.68
     1565517.688      420886.285
#Sta/Elev= 30
      10  717.52    29.9  720.63    79.7  725.08    89.6   725.1    99.6  722.88
   179.2   691.7   258.9  662.86   268.8  660.03   288.8  657.59   298.7  655.42
   318.6  647.51   328.6  644.59   338.5  643.21   368.4  640.82   398.2  636.24
   408.2     636   418.2  636.03   428.1  636.35   467.9  640.64   537.6  644.71
   587.3  649.14   607.2  649.68     647  647.82     657  649.45   666.9  652.97
   716.7  678.04   736.6  687.43   756.5  695.98   786.4  707.34   826.2  717.44
#Mann= 3 , 0 , 0
       0     .08       0   398.2    .045       0   418.2     .08       0
Bank Sta=398.2,418.2
XS Rating Curve= 0 ,0
Exp/Cntr=0.3,0.1

Type RM Length L Ch R = 1 ,6790.2  ,120.3,120.1,121.6
XS GIS Cut Line= 3
     1564934.638      421570.596     1565399.566      421389.148
     1565764.995      421237.934
#Sta/Elev= 30
      10  773.08   109.8  729.32   199.6   691.9   239.6  676.84   319.4  649.77
   329.4  647.74   349.4  645.57   359.3  645.04   369.3  645.68   389.3  648.97
   399.3  648.76   409.2   647.5   439.2  641.88   459.2   637.1   469.1  636.03
   479.1  635.99   489.1  636.12   519.4  639.49   549.8  642.02   570.1  644.77
   580.2  646.89   620.8  659.22   661.3  673.67   691.7  686.07   762.7  716.31
     783  724.15   823.6  738.28   843.9  745.94   874.3  758.35   894.6   767.3
#Mann= 3 , 0 , 0
       0     .08       0   469.1    .045       0   489.1     .08       0
Bank Sta=469.1,489.1
XS Rating Curve= 0 ,0
Exp/Cntr=0.3,0.1

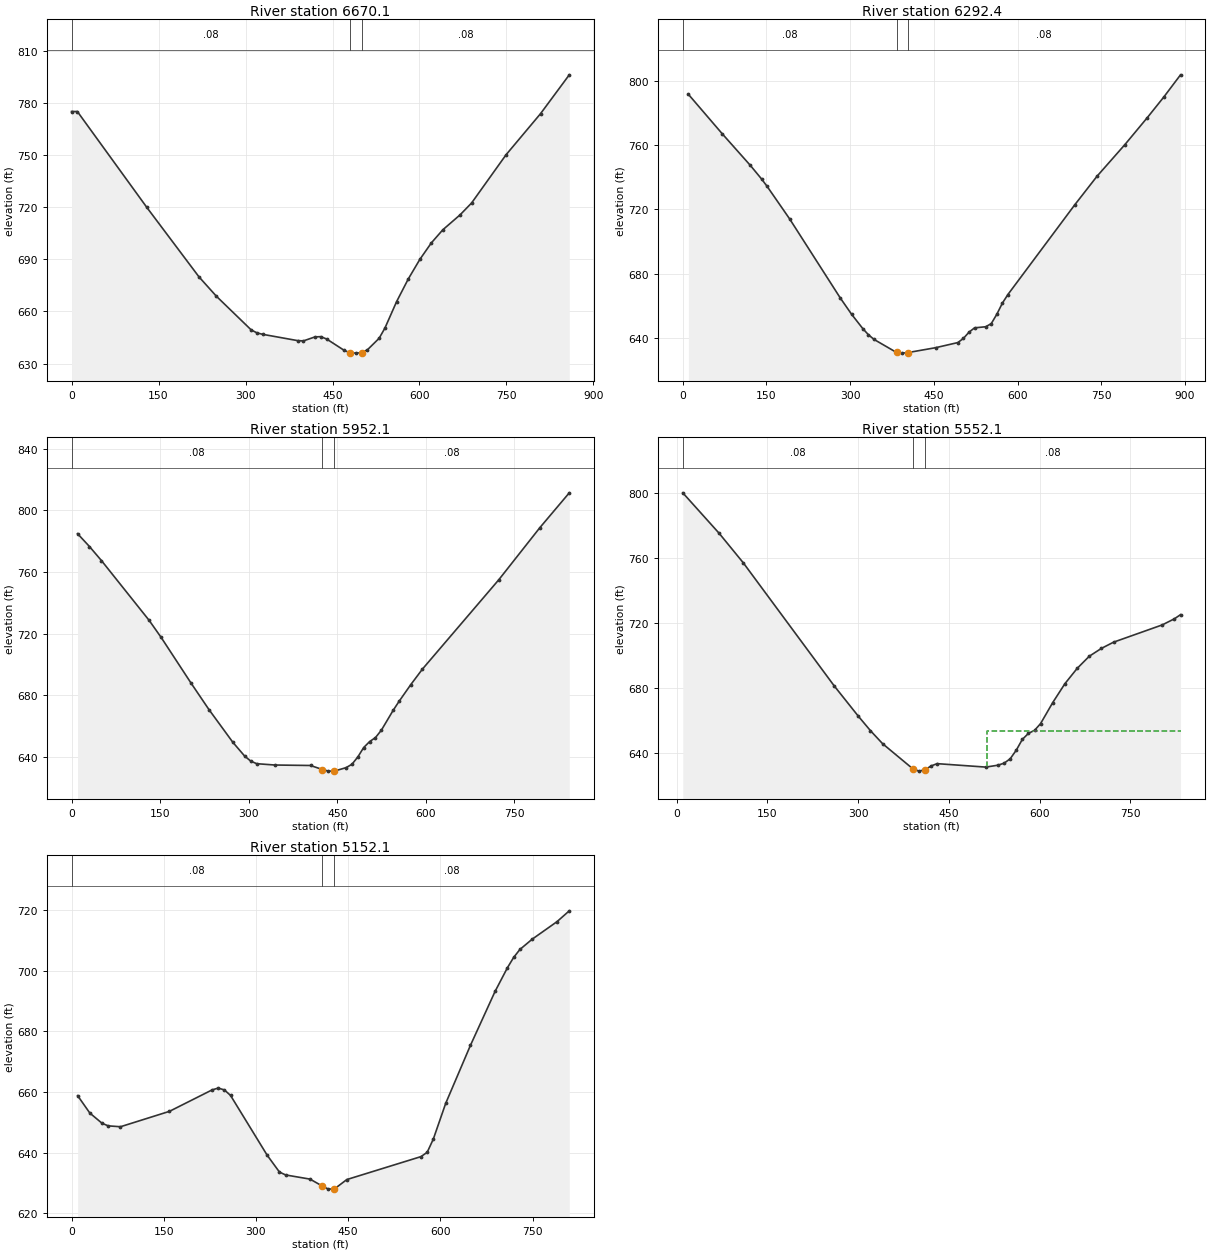
Type RM Length L Ch R = 1 ,6670.1  ,388.8,377.7,367.9
XS GIS Cut Line= 4
     1564943.226      421649.367     1565292.977      421501.505
     1565503.396      421515.723     1565770.685      421501.505
#Sta/Elev= 30
       0  775.21      10  775.21   129.9  719.91   219.8   679.9   249.8  668.75
   309.8  649.35   319.8  647.64   329.8   646.8   389.8  643.19   399.8  643.03
   419.9  645.34   429.9  645.47     440  644.09   470.1  637.58   480.2   636.2
   490.2  635.98   500.2   636.2   510.3  637.93   530.4  644.54   540.4  650.43
   560.5  665.65   580.6  678.69   600.5  689.94   620.4  699.49   640.2  707.05
   669.9  715.64   689.8  722.48   749.2  750.26   808.7  773.96   858.3  796.35
#Mann= 3 , 0 , 0
       0     .08       0   480.2    .045       0   500.2     .08       0
Bank Sta=480.2,500.2
XS Rating Curve= 0 ,0
Exp/Cntr=0.3,0.1

Type RM Length L Ch R = 1 ,6292.4  ,338.6,340.3,341.3
XS GIS Cut Line= 3
      1564967.85      421953.842     1565333.318      421808.687
     1565806.618      421650.826
#Sta/Elev= 30
    10.1  791.52    70.6  767.07     121  747.41   141.2  738.94   151.2  734.32
   191.6  714.09   282.3  664.99   302.5   654.9   322.7  645.94   332.7  642.16
   342.8  639.24   383.2  631.12   393.2  630.72   403.2  631.04   453.1  634.09
     493  637.28     503  639.87     513  643.72     523  646.43   542.9  647.11
   552.9  649.04   562.9  654.87   572.9   661.8   582.8  667.15   702.6  722.88
   742.5  740.63   792.4  760.27   832.3  776.91   862.2  789.86   892.2  803.66
#Mann= 3 , 0 , 0
       0     .08       0   383.2    .045       0   403.2     .08       0
Bank Sta=383.2,403.2
XS Rating Curve= 0 ,0
Exp/Cntr=0.3,0.1

Type RM Length L Ch R = 1 ,5952.1  ,403.6,400,395.9
XS GIS Cut Line= 3
     1565086.435      422206.897     1565512.912      422079.823
     1565896.866      421975.797
#Sta/Elev= 30
    10.1  784.91    30.3  776.55    50.6  767.43   131.5  728.54   151.7  717.53
   202.3  687.89   232.6  670.72   273.1  649.45   293.3  640.41   303.4  637.24
   313.5  635.55   343.9  634.69   404.6  634.38   424.9  631.76   434.9  630.72
   444.9  630.74   464.9  632.98   474.8  635.18   484.8  639.96   494.7  646.05
   504.7  649.89   514.6  652.49   524.6   657.3   544.5  670.15   554.4  675.93
   574.3  686.82   594.2  696.99   723.5     755   793.1  788.85   842.8   811.4
#Mann= 3 , 0 , 0
       0     .08       0   424.9    .045       0   444.9     .08       0
Bank Sta=424.9,444.9
XS Rating Curve= 0 ,0
Exp/Cntr=0.3,0.1

Type RM Length L Ch R = 1 ,5552.1  ,406.1,400,392
XS GIS Cut Line= 3
     1565169.288      422638.182     1565540.999      422464.428
     1565925.358      422289.206
#Sta/Elev= 30
      10  800.09    70.1  775.18   110.1  756.97   260.2  681.32   300.2   662.6
   320.2  653.73   340.3   645.7   390.3  630.24   400.3  628.83   410.3  629.66
   420.4  632.01   430.4  633.43   510.9  631.31     531  632.49   541.1  633.73
   551.1   636.4   561.2  641.72   571.2  648.34   581.3  652.07   591.4  653.92
   601.4  658.09   621.5  671.03   641.6  682.64   661.8  692.03   681.9  699.54
     702  704.37   722.1   708.2   802.6  718.83   822.7   722.6   832.7  725.12
#Mann= 3 , 0 , 0
      10     .08       0   390.3    .045       0   410.3     .08       0
#XS Ineff= 2 , 0
                          513.51          653.46
Permanent Ineff=
       F       F
Bank Sta=390.3,410.3
XS Rating Curve= 0 ,0
Exp/Cntr=0.3,0.1

Type RM Length L Ch R = 1 ,5152.1  ,5166.1,5152.1,5139.9
XS GIS Cut Line= 3
     1565392.838      423062.324     1565727.366      422795.738
     1566009.335      422537.986
#Sta/Elev= 30
     9.9  658.83    29.8  653.08    49.7  649.71    59.7  648.87    79.6  648.58
   159.2  653.65   228.8  660.74   238.7  661.33   248.7  660.71   258.6  658.92
   318.3  639.18   338.2  633.65   348.2  632.69     388  631.31   407.8  629.04
   417.8  628.01   427.8   628.1   447.9  631.17   568.5  638.73   578.6  640.15
   588.6  644.52   608.7  656.28   648.9  675.38   689.1  693.22   709.2  701.03
   719.3  704.41   729.4  707.02   749.5  710.43   789.7  716.18   809.8  719.77
#Mann= 3 , 0 , 0
       0     .08       0   407.8    .045       0   427.8     .08       0
Bank Sta=407.8,427.8
XS Rating Curve= 0 ,0
Exp/Cntr=0.3,0.1
Stream Node=CENLYNNCR       ,Main            , 0 , 0 ,Upstream end
Stream Node=CENLYNNCR       ,Main            , 0 , 1 ,Downstream end

Chan Stop Cuts=-1
Use User Specified Reach Order=0